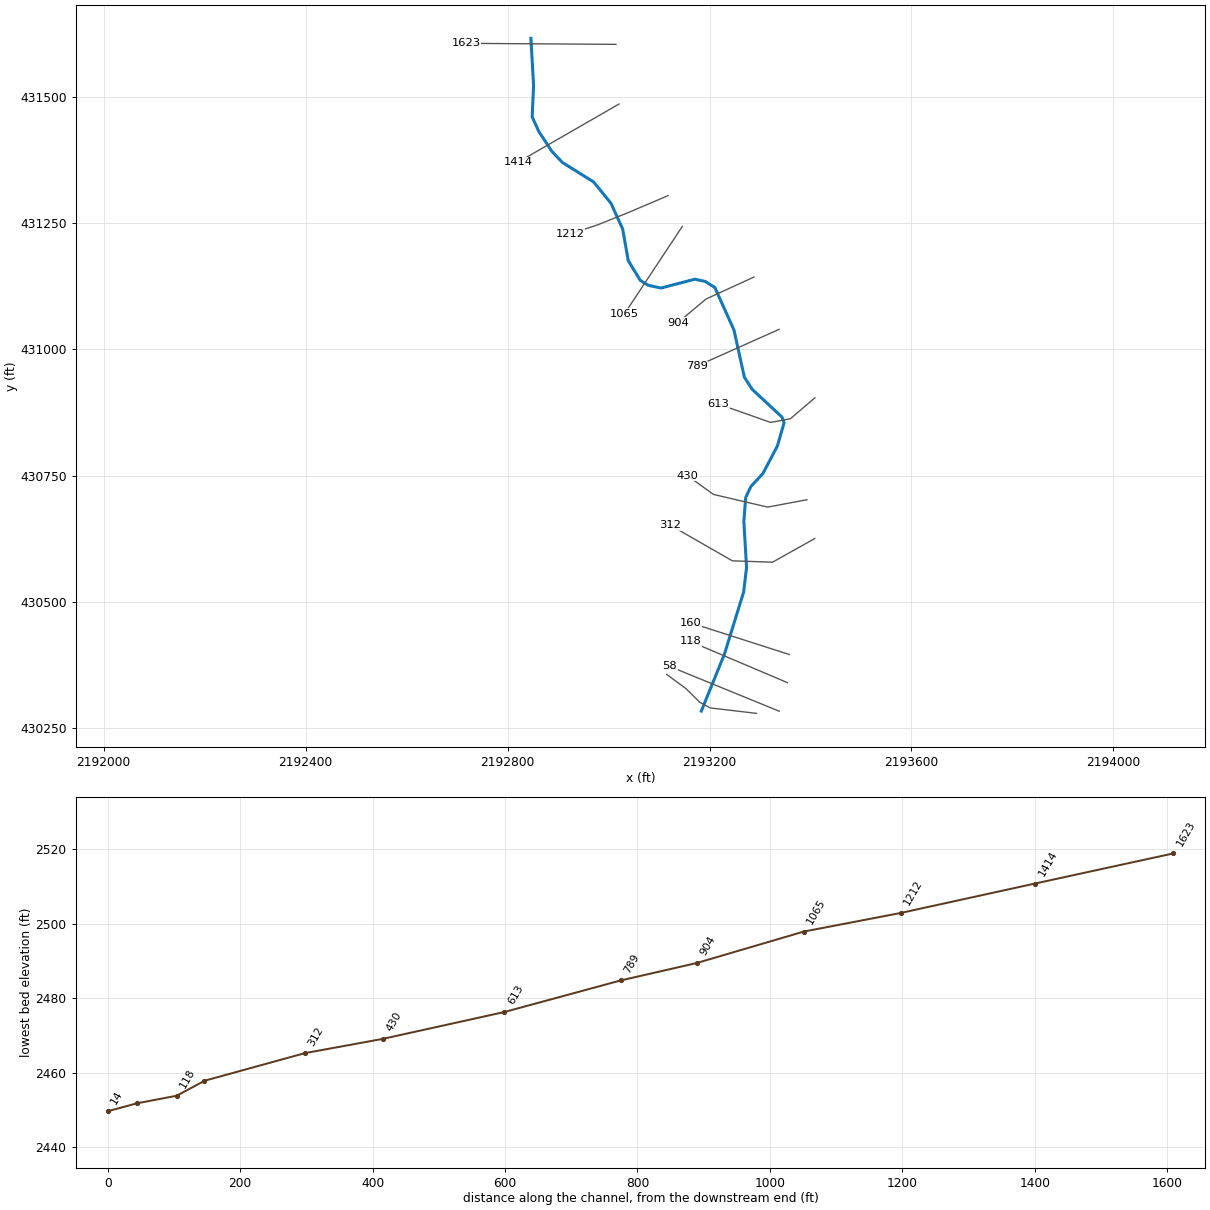
--- BLUELCKRN.prj (project) ---

Proj Title=BLUELCKRN
Current Plan=p01
Default Exp/Contr=0,0
English Units
Geom File=g01
Flow File=f01
Plan File=p01
BEGIN DESCRIPTION:
----------MODEL BY WOOD PLC 2021----------
Stream Name: Blue Lick Run
Flood Zone: Enhanced Approximate
Pocahontas County, WV
HEC-RAS Version: RAS 6.1
Vertical Datum: NAVD88
Projection: NAD 1983 StatePlane West Virginia S FIPS 4702 (US Feet)
Terrain: 1-meter LIDAR (FEMA Region III 3DEP collected 2016-2018)
Land Use: 2019 NLCD
Hydrologic Method:
WV SIR2010-5033 regression equations
Model Notes:
Normal Depth tie in to Stamping Creek
END DESCRIPTION:
DSS File=dss
DSS Export Rating Curves= 0
DSS Export Rating Curve Sorted= 0
DSS Export Volume Flow Curves= 0
DXF OffsetX= 0
DXF OffsetY= 0
DXF ScaleX= 0
DXF ScaleY= 0

--- BLUELCKRN.p01 (plan) ---

Plan Title=Floodplain
Program Version=6.10
Short Identifier=Floodplain
Geom File=g01
Flow File=f01
Subcritical Flow
K Sum by GR= 0
Std Step Tol= 0.01
Critical Tol= 0.01
Num of Std Step Trials= 20
Max Error Tol= 0.3
Flow Tol Ratio= 0.001
Split Flow NTrial= 30
Split Flow Tol= 0.02
Split Flow Ratio= 0.02
Log Output Level= 0
Friction Slope Method= 1
Unsteady Friction Slope Method= 2
Unsteady Bridges Friction Slope Method= 1
Parabolic Critical Depth
Global Vel Dist= 0 , 0 , 0
Global Log Level= 0
CheckData=True
Encroach Param=-1 ,0,0, 0
Computation Interval=0.1SEC
Output Interval=1SEC
Instantaneous Interval=Max Profile
Mapping Interval=1HOUR
Computation Time Step Use Courant=        0
Computation Time Step Use Time Series=    0
Computation Time Step Count To Double=0
Computation Time Step Max Doubling=0
Computation Time Step Max Halving=0
Computation Time Step Residence Courant=0
Run HTab= 0
Run UNet= 0
Run Sediment= 0
Run PostProcess= 0
Run WQNet= 0
Run RASMapper=-1
UNET Theta= 0
UNET Theta Warmup= 0
UNET ZTol= 0
UNET ZSATol= 0
UNET MxIter= 0
UNET Max Iter WO Improvement= 0
UNET MaxInSteps= 0
UNET DtIC= 0
UNET DtMin= 0
UNET MaxCRTS= 0
UNET WFStab= 0
UNET SFStab= 0
UNET WFX= 1
UNET SFX= 1
UNET Gravity=32.174
UNET 1D Methodology=Finite Difference
UNET DSS MLevel= 1
UNET Pardiso=0
UNET DZMax Abort= 0
UNET Use Existing IB Tables= 0
UNET Froude Reduction=False
UNET Froude Limit= 0
UNET Froude Power= 0
UNET D1 Cores= 0
UNET WindReference=Eulerian
UNET WindDragFormulation=Hsu (1988)
UNET D2 Coriolis=0
UNET D2 Cores= 0
UNET D2 Theta= 1
UNET D2 Theta Warmup= 1
UNET D2 Z Tol= 0.01
UNET D2 Volume Tol= 0.01
UNET D2 Max Iterations= 20
UNET D2 Equation= 0
UNET D2 RampUpFraction=0.1
UNET D2 TimeSlices= 1
UNET D2 Turbulence Formulation=Non-Conservative (original)
UNET D2 Eddy Viscosity=0.3
UNET D2 Transverse Eddy Viscosity=0.1
UNET D2 Smagorinsky Mixing=0
UNET D2 BCVolumeCheck=0
UNET D2 Cores=0
UNET D2 SolverType=PARDISO (Direct)
UNET D2 Minimum Iterations= 2147483647
UNET D2 Maximum Iterations= 2147483647
UNET D2 Restart Number= 10
UNET D2 Relaxation Coeff=1.3
UNET D2 SOR Precondition Iterations= 10
UNET D2 ILUT Maximum Fill= 8
UNET D2 ILUT Tolerance=1E-08
UNET D1D2 MaxIter= 0
UNET D1D2 ZTol=0.01
UNET D1D2 QTol=0.1
UNET D1D2 MinQTol=1
DSS File=dss
Write IC File= 0
Write IC File at Fixed DateTime=0
Write IC File at Sim End=0
Echo Input=False
Echo Parameters=False
Echo Output=False
Write Detailed= 0
HDF Write Warmup=0
HDF Write Time Slices=0
HDF Flush=0
HDF Compression= 1
HDF Chunk Size= 1
HDF Spatial Parts= 1
HDF Use Max Rows=0
HDF Fixed Rows= 1
Calibration Method= 0
Calibration Iterations= 20
Calibration Max Change=0.05
Calibration Tolerance=0.2
Calibration Maximum=1.5
Calibration Minimum=0.5
Calibration Optimization Method= 1
WQ AD Non Conservative
WQ ULTIMATE=-1
WQ Max Comp Step=1HOUR
WQ Output Interval=15MIN
WQ Output Selected Increments= 0
WQ Output face flow=0
WQ Output face velocity=0
WQ Output face area=0
WQ Output face dispersion=0
WQ Output cell volume=0
WQ Output cell surface area=0
WQ Output cell continuity=0
WQ Output cumulative cell continuity=0
WQ Output face conc=0
WQ Output face dconc_dx=0
WQ Output face courant=0
WQ Output face peclet=0
WQ Output face adv mass=0
WQ Output face disp mass=0
WQ Output cell mass=0
WQ Output cell source sink temp=0
WQ Output nsm pathways=0
WQ Output nsm derived pathways=0
WQ Create Restart=0
WQ Fixed Restart=0
WQ System Summary=0
WQ Write To DSS=0
Sorting and Armoring Iterations= 10
XS Update Threshold= 0.02
Bed Roughness Predictor= 0
Hydraulics Update Threshold= 0.02
Energy Slope Method= 1
Volume Change Method= 1
Sediment Retention Method= 0
Sediment TS Multiplier= 1
Warm Up Method= 0
XS Weighting Method= 0
Number of US Weighted Cross Sections= 1
Number of DS Weighted Cross Sections= 1
Upstream XS Weight=0
Main XS Weight=1
Downstream XS Weight=0
Number of DS XS's Weighted with US Boundary= 1
Upstream Boundary Weight= 1
Weight of XSs Associated with US Boundary= 0
Number of US XS's Weighted with DS Boundary= 1
Downstream Boundary Weight= 0.5
Weight of XSs Associated with DS Boundary= 0.5
Percentile Method= 0
Sediment Output Level= 3
Mass or Volume Output= 0
Output Increment Type= 1
Profile and TS Output Increment= 1
Transport Output Increment 1
XS Output Flag= 0
XS Output Increment= 10
Read HDF5 Sediment Hotstart= 0
Sediment Hotstart Type= 0
Write Gradation File= 0
Read Gradation Hotstart= 0
Write HDF5 File= 1
Write Binary Output= 1
Write DSS Sediment File= 0
DSS Sediment Output Type= 1
SV Curve= 0
Specific Gage Flag= 0
Subcell Erosion Methods= 0
Subcell Deposition Methods= 0
Advection Scheme= 1
Matrix Solver= 0
Implicit Weighting Factor= 1
Maximum Outer Loop Convergence Iterations= 5
Convergence Maximum Absolute= 0.001
Convergence RMSE= 0.0001
Grain Fractions Max Abs Error= 0.001
Max Subgrid Regions= 1
Max Subgrid Length Scale= 3.402823E+38
Initial Layer Thickness= 3.402823E+38
Min Layer Thickness= 3.402823E+38
Max Layer Thickness= 3.402823E+38
Number of Layers= 5

--- BLUELCKRN.f01 (steady flow) ---

Flow Title=Flow
Program Version=6.10
Number of Profiles= 6
Profile Names=01pct,10pct,04pct,02pct,0_2pct,01plus
River Rch & RM=BLUELCKRN,Main            ,1623
     533     281     374     451     745     788
Boundary for River Rch & Prof#=BLUELCKRN,Main            , 1
Up Type= 0
Dn Type= 3
Dn Slope=0.02754
Boundary for River Rch & Prof#=BLUELCKRN,Main            , 2
Up Type= 0
Dn Type= 3
Dn Slope=0.02754
Boundary for River Rch & Prof#=BLUELCKRN,Main            , 3
Up Type= 0
Dn Type= 3
Dn Slope=0.02754
Boundary for River Rch & Prof#=BLUELCKRN,Main            , 4
Up Type= 0
Dn Type= 3
Dn Slope=0.02754
Boundary for River Rch & Prof#=BLUELCKRN,Main            , 5
Up Type= 0
Dn Type= 3
Dn Slope=0.02754
Boundary for River Rch & Prof#=BLUELCKRN,Main            , 6
Up Type= 0
Dn Type= 3
Dn Slope=0.02754
DSS Import GetInterval= 0
DSS Import GetPeak= 0
DSS Import FillOption= 0

--- BLUELCKRN.g01 (geometry) ---

Geom Title=Geometry
Program Version=6.10

River Reach=BLUELCKRN       ,Main
Reach XY= 30
     2192846.222      431616.028     2192851.566      431523.218
     2192848.777      431460.545     2192862.004      431431.277
     2192887.669      431392.309     2192908.693      431370.073
     2192970.354      431331.668     2193004.895      431289.255
     2193027.947      431238.533     2193038.973      431175.948
     2193062.799      431136.759     2193078.371      431126.978
     2193103.745      431121.468     2193170.957      431138.991
      2193191.29      431134.571     2193210.512      431122.616
     2193248.417      431038.306     2193268.949      430945.196
     2193284.224       430921.142193343.34254134430866.089332675
2193347.66879316430854.751569281     2193334.396      430808.653
     2193305.851      430754.305     2193281.837       430728.36
     2193271.642       430706.53     2193267.976      430659.257
     2193273.359      430568.252     2193267.498      430519.276
     2193229.524      430396.454     2193183.785      430283.713

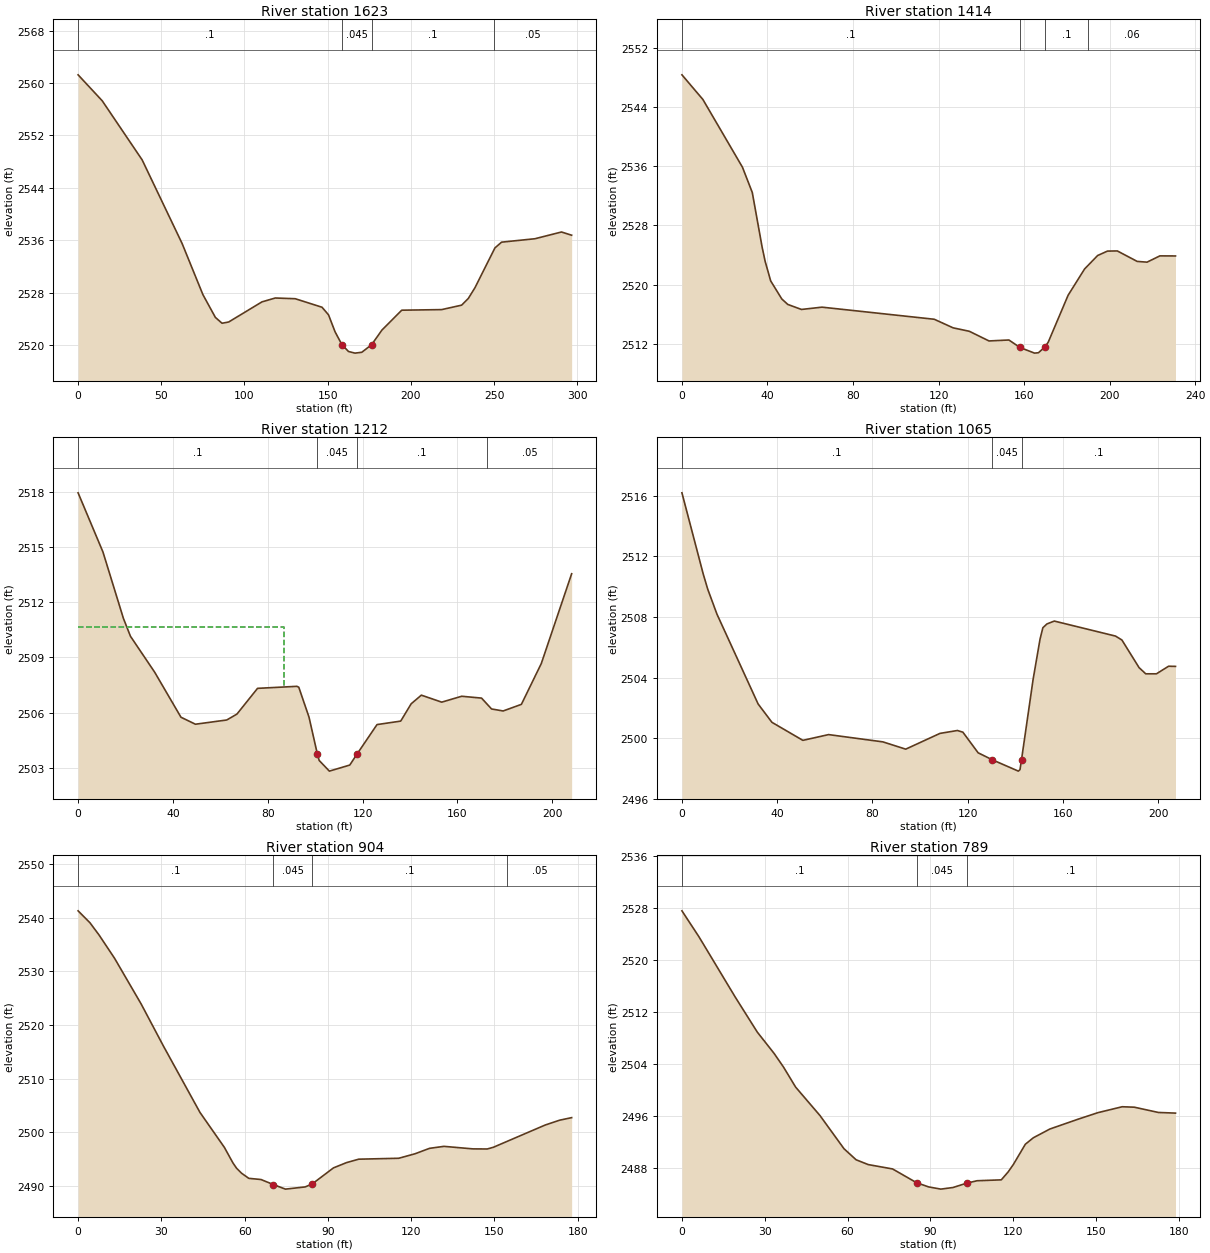
Type RM Length L Ch R = 1 ,1623    ,209.2,209.2,209.2
XS GIS Cut Line= 2
2193014.64745733431604.0987603382192718.04964451431606.102799614
#Sta/Elev= 30
       0 2561.24    14.5 2557.28    38.5 2548.26    62.5 2535.51      75 2527.71
    82.5 2524.23    86.5 2523.34    90.5 2523.53   110.5  2526.6   118.5 2527.19
   130.5 2527.08   146.6 2525.78   150.5 2524.62   154.4 2522.05   158.5 2520.09
   162.5 2519.03   166.4 2518.78   170.5 2518.91  176.372520.059   182.6  2522.3
   194.5 2525.33   218.5 2525.42   230.5  2526.1   234.5 2527.12   238.5 2528.76
   250.5 2534.83   254.5 2535.71   274.5 2536.23   290.5 2537.26   296.6 2536.77
#Mann= 4 ,-1,0
       0      .1       0   158.5    .045       0  176.37      .1       0
     250     .05       0
Bank Sta=158.5,176.37
XS Rating Curve= 0 ,0
Exp/Cntr(USF)=0,0
Exp/Cntr=0.3,0.1

Type RM Length L Ch R = 1 ,1414    ,205.3,202.7,199.7
XS GIS Cut Line= 2
2193020.65957515431485.8604430682192820.65645543431370.728386675
#Sta/Elev= 30
       0 2548.42     9.8 2545.08    28.3  2535.9    32.9 2532.47    37.5 2525.07
    38.9 2523.16    41.5 2520.49    46.7 2518.04    49.5  2517.3    55.9 2516.62
    65.5 2516.93     118 2515.29   126.8 2514.13   134.4 2513.66   143.6 2512.35
   152.9 2512.48158.06732511.467   164.9  2510.7   166.7 2510.75   169.7 2511.52
   171.3 2512.19   180.6 2518.55   188.3 2522.11   194.4 2523.93     199 2524.53
   203.6 2524.55   212.9 2523.13   217.5 2523.03   223.5 2523.88   230.8 2523.87
#Mann= 4 ,-1,0
       0      .1       0158.0673    .045       0   169.7      .1       0
     190     .06       0
Bank Sta=158.0673,169.7
XS Rating Curve= 0 ,0
Exp/Cntr(USF)=0,0
Exp/Cntr=0.3,0.1

Type RM Length L Ch R = 1 ,1212    ,140.2,146.5,153.5
XS GIS Cut Line= 4
2193117.85548003431304.4948886112193037.42158813 431270.24462607
2192976.99380727431246.102338368 2192923.9759492431228.847396425
#Sta/Elev= 30
       0 2517.95    10.5 2514.73    19.1 2511.13    22.1 2510.15    32.3  2508.2
    43.4 2505.75    49.5 2505.37    62.7  2505.6      67 2505.92    75.7 2507.32
    92.3 2507.43    93.1 2507.38    97.4 2505.76100.92612503.755   101.7  2503.4
     106 2502.82   114.6 2503.15117.7851 2503.77   126.1 2505.35   136.1 2505.54
   140.5 2506.48   144.8 2506.95   153.4 2506.57   161.8 2506.89   170.2 2506.79
   174.4  2506.2   179.3 2506.09     187 2506.45   195.4 2508.67   208.2 2513.55
#Mann= 4 ,-1,0
       0      .1       0100.9261    .045       0117.7851      .1       0
  172.49     .05       0
#XS Ineff= 2 , 0
           87.04 2510.68
Permanent Ineff=
       F       F
Bank Sta=100.9261,117.7851
XS Rating Curve= 0 ,0
Exp/Cntr(USF)=0,0
Exp/Cntr=0.3,0.1

Type RM Length L Ch R = 1 ,1065    ,168,161.2,153.5
XS GIS Cut Line= 2
2193146.16277153431243.5791645782193031.72210869431070.700716454
#Sta/Elev= 30
       0 2516.19     8.9 2510.86    10.8 2509.85    14.7 2508.19      32 2502.26
    37.8 2501.05    50.8 2499.86    61.6 2500.24    84.4 2499.76      94 2499.28
   108.4 2500.32   115.7 2500.51     118  2500.4   124.4 2499.04   130.2 2498.59
   141.3 2497.83     142 2497.93  142.642498.593   147.5 2503.88   150.4 2506.53
   151.6 2507.29   153.3 2507.54   156.4 2507.73   182.1 2506.74   184.8 2506.48
     192 2504.66   194.8 2504.25   199.3 2504.25   204.4 2504.75   207.3 2504.74
#Mann= 3 ,-1,0
       0      .1       0   130.2    .045       0  142.64      .1       0
Bank Sta=130.2,142.64
XS Rating Curve= 0 ,0
Exp/Cntr(USF)=0,0
Exp/Cntr=0.3,0.1

Type RM Length L Ch R = 1 ,904     ,115.3,115.1,115.5
XS GIS Cut Line= 3
2193288.08305395431143.3180536162193193.04136848431099.690877075
2193136.88208303431052.692784141
#Sta/Elev= 30
       0 2541.28     4.3 2539.04     7.6 2536.74    13.1 2532.47    22.7 2523.94
    30.7 2516.12    43.9 2503.72    52.7  2497.2    55.8 2494.29    57.1 2493.31
    58.9 2492.38    61.5 2491.43    65.9 2491.21    70.3 2490.28    74.7 2489.42
    81.8 2489.83   84.32 2490.38      92 2493.38    96.7 2494.36   101.1    2495
   115.5 2495.17   121.4 2496.01   126.6 2497.02   131.8 2497.39   142.2 2496.92
   147.4  2496.9   149.6 2497.22   168.3 2501.37   173.5 2502.27   177.8 2502.74
#Mann= 4 ,-1,0
       0      .1       0    70.3    .045       0   84.32      .1       0
  154.58     .05       0
Bank Sta=70.3,84.32
XS Rating Curve= 0 ,0
Exp/Cntr(USF)=0,0
Exp/Cntr=0.3,0.1

Type RM Length L Ch R = 1 ,789     ,177.7,175.5,173.3
XS GIS Cut Line= 2
2193337.80934085431039.6485472842193174.57002827430966.811320398
#Sta/Elev= 30
       0 2527.61     6.2 2523.59    19.3 2514.33    27.3 2508.93    33.4 2505.64
    36.8 2503.54    41.2 2500.45      50 2496.08    58.7 2490.97    63.1 2489.26
    67.5 2488.52    76.3 2487.85      85 2485.73    89.4 2485.08    93.8 2484.74
    98.2 2484.99   103.1 2485.65   106.9 2486.03   115.7 2486.17   118.2  2487.4
   120.1 2488.56   124.4 2491.65   127.3 2492.65   133.3    2494   143.5 2495.51
   150.7 2496.52   159.5 2497.43   163.9 2497.36   172.6 2496.55   178.8 2496.45
#Mann= 3 ,0,0
       0      .1       0      85    .045       0   103.1      .1       0
Bank Sta=85,103.1
XS Rating Curve= 0 ,0
Exp/Cntr(USF)=0,0
Exp/Cntr=0.3,0.1

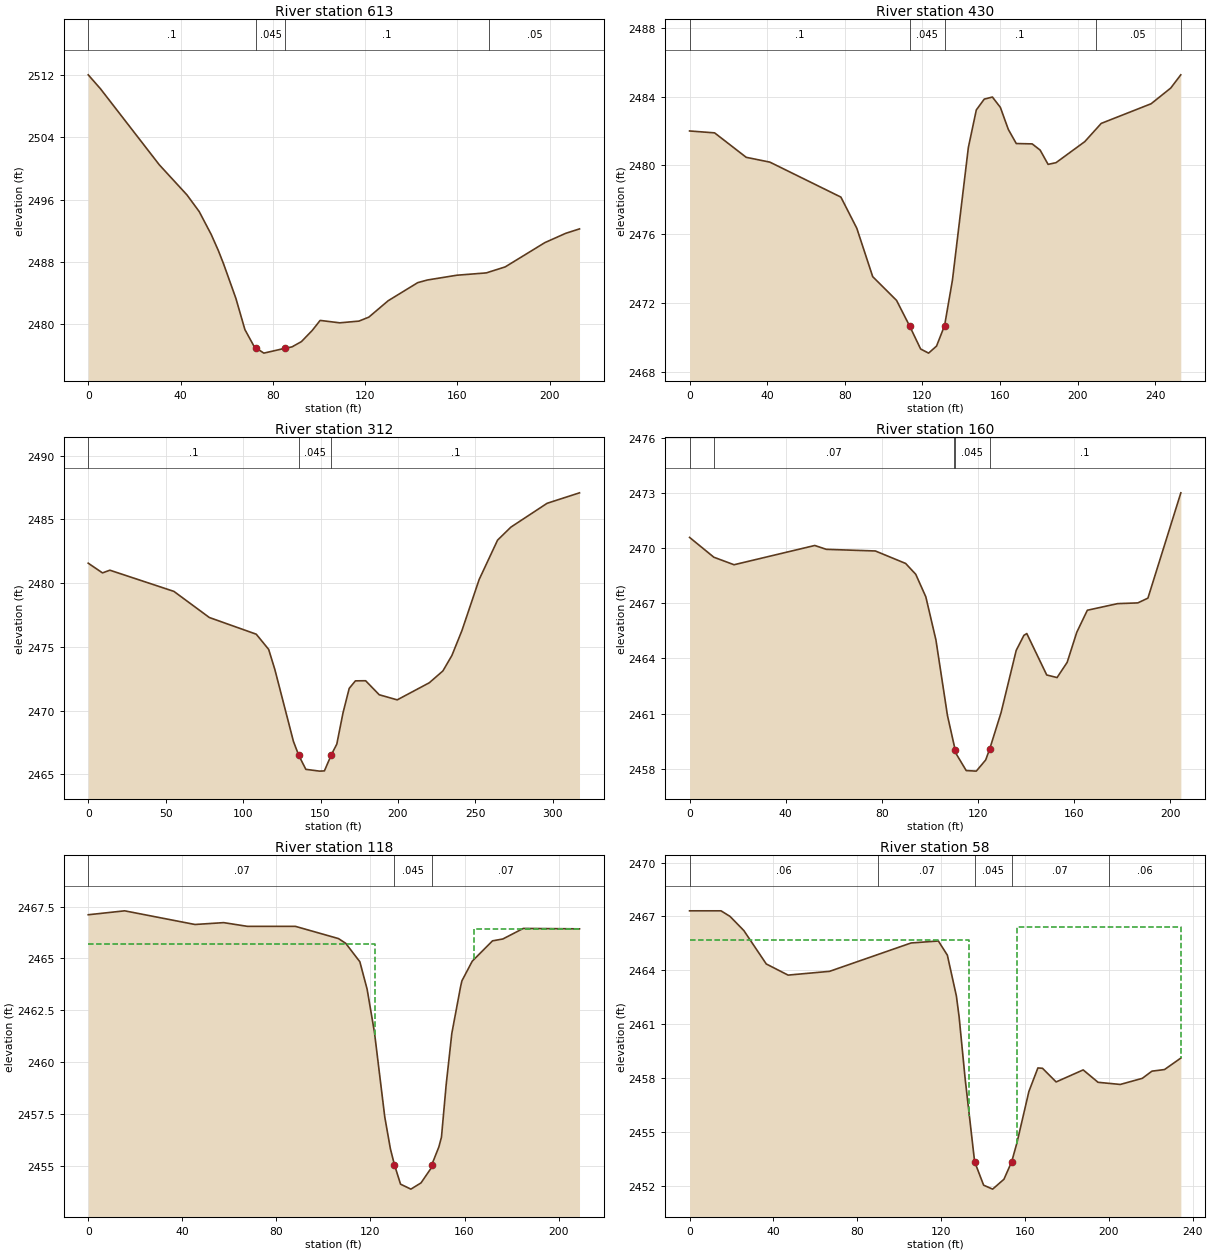
Type RM Length L Ch R = 1 ,613     ,185.1,183.3,177.5
XS GIS Cut Line= 4
2193408.71413036430904.1188295192193360.07200962430862.552735376
2193320.93263909430855.3361114492193218.02567979430891.653178414
#Sta/Elev= 30
       0 2512.02     5.3 2510.23    30.8 2500.47    42.8  2496.6    48.1 2494.46
    53.3 2491.52    56.4 2489.45    58.6 2487.79      64 2483.31    67.9 2479.31
      72 2477.0972.815122476.937    76.1 2476.29 85.14112476.903    88.3 2477.09
    92.4 2477.77    97.1 2479.21   100.5 2480.49     109 2480.18   117.3  2480.4
   121.6 2480.91     130 2483.02   142.8 2485.34     147 2485.68   159.7 2486.29
   172.5 2486.59   180.7 2487.36   197.9 2490.48   206.9 2491.67   212.9 2492.24
#Mann= 4 ,-1,0
       0      .1       072.81512    .045       0 85.1411      .1       0
  173.78     .05       0
Bank Sta=72.81512,85.1411
XS Rating Curve= 0 ,0
Exp/Cntr(USF)=0,0
Exp/Cntr=0.3,0.1

Type RM Length L Ch R = 1 ,430     ,114.7,118.2,120.1
XS GIS Cut Line= 4
2193392.82966749430702.2234728912193314.98304012430687.608568498
2193207.84710044430712.7692816052193155.90240241430750.104533313
#Sta/Elev= 30
       0    2482    12.9 2481.89    29.2 2480.47    41.4 2480.19      78 2478.16
    86.2 2476.35    94.4 2473.54   106.7 2472.16113.41092470.678   119.1 2469.34
   123.2  2469.1   127.3 2469.51131.44092470.697   135.5 2473.34   143.7 2481.04
   147.8 2483.22   151.9 2483.85   156.1 2483.97   160.2 2483.37   164.3 2482.09
   168.4 2481.27   176.6 2481.25   180.7 2480.89   184.8 2480.06   188.9 2480.16
   203.7 2481.38   212.2 2482.44   237.9 2483.58     248 2484.49   253.2 2485.26
#Mann= 5 ,-1,0
       0      .1       0113.4109    .045       0131.4409      .1       0
  209.26     .05       0  253.23      .1       0
Bank Sta=113.4109,131.4409
XS Rating Curve= 0 ,0
Exp/Cntr(USF)=0,0
Exp/Cntr=0.3,0.1

Type RM Length L Ch R = 1 ,312     ,156,151.5,148.2
XS GIS Cut Line= 4
2193408.41663963 430625.40196732 2193324.8771896 430578.56015091
2193245.32875439430581.1898512482193122.28130057 430651.78931669
#Sta/Elev= 30
       0 2481.57     9.2 2480.81      14 2481.02    55.3 2479.36    78.2 2477.31
   108.5    2476   116.5 2474.81   120.5 2473.23   132.5 2467.59135.90252466.503
   140.5  2465.4   149.4 2465.26   152.5 2465.28156.99972466.552   160.5 2467.38
   164.5 2469.83   168.5 2471.75   172.5 2472.34   179.1 2472.35   187.9 2471.25
   199.5 2470.85   220.2 2472.19     229 2473.12   234.8 2474.33   241.3 2476.29
   252.4 2480.29   264.3 2483.38   272.9  2484.4   296.3 2486.27   317.2 2487.09
#Mann= 3 ,-1,0
       0      .1       0135.9025    .045       0156.9997      .1       0
Bank Sta=135.9025,156.9997
XS Rating Curve= 0 ,0
Exp/Cntr(USF)=0,0
Exp/Cntr=0.3,0.1

Type RM Length L Ch R = 1 ,160     ,43.2,41.8,41.1
BEGIN DESCRIPTION:
structure xs 4
END DESCRIPTION:
XS GIS Cut Line= 2
2193357.74844382430395.7959774422193163.15061883430458.251360462
#Sta/Elev= 30
       0  2470.6    10.1 2469.52    18.5 2469.11    52.1 2470.16    56.9 2469.95
    77.3 2469.86    89.9 2469.18    94.1 2468.59    98.3 2467.36   102.5 2465.01
   107.3 2460.89   110.5 2459.02   110.9 2458.81   115.1 2457.89   119.3 2457.86
   123.2 2458.47  124.822459.047   129.6 2461.05   135.9 2464.44   139.1 2465.26
   140.3 2465.36   148.6  2463.1   152.9 2462.96   157.1 2463.79   161.1 2465.43
   165.5 2466.63   178.1 2466.99   186.5 2467.03   190.7 2467.29   204.4 2473.03
#Mann= 5 ,-1,0
       0     .06       0      10     .07       0     110      .1       0
   110.5    .045       0  124.82      .1       0
Bank Sta=110.5,124.82
XS Rating Curve= 0 ,0
Exp/Cntr(USF)=0,0
Exp/Cntr=0.5,0.3

Type RM Length L Ch R = 1 ,118     ,60.2,60.3,60.5
BEGIN DESCRIPTION:
structure xs 3; 7.7 ft between structure and xs
END DESCRIPTION:
XS GIS Cut Line= 2
 2193354.4613184430339.9148452672193162.15350968430421.510366999
#Sta/Elev= 30
       0 2467.11    15.5  2467.3    45.4 2466.64    57.6 2466.73    67.7 2466.55
    88.1 2466.55   106.4 2465.96   109.5 2465.73   115.5 2464.84   118.6 2463.51
   121.7 2461.44   126.1 2457.34   128.5  2455.8   130.2 2455.04   132.8  2454.1
   137.2 2453.86   141.5 2454.16   145.9 2454.89   146.1 2455.04   149.1  2455.9
   150.2 2456.37   152.2  2458.9   154.6 2461.38   158.3 2463.62   158.9 2463.92
   163.3 2464.87   171.9 2465.85   176.3 2465.94     185 2466.45   208.9 2466.43
#Mann= 3 ,-1,0
       0     .07       0   130.2    .045       0   146.1     .07       0
#XS Ineff= 2 , 0
             122  2465.7     164          2466.4
Permanent Ineff=
       F       F
Bank Sta=130.2,146.1
XS Rating Curve= 0 ,0
Exp/Cntr(USF)=0,0
Exp/Cntr=0.5,0.3

Type RM Length L Ch R = 1 ,58      ,45.5,44.1,43.8
BEGIN DESCRIPTION:
structure xs 2; 7.3 ft between structure and xs
END DESCRIPTION:
XS GIS Cut Line= 2
2193338.02569129430283.3762880072193121.07541343430372.128674403
#Sta/Elev= 30
       0 2467.31      15 2467.31    19.3    2467    25.9 2466.21    36.6 2464.35
      47 2463.73    66.8 2463.94   105.7 2465.52   118.7 2465.63     123 2464.84
   127.3 2462.57   128.6 2461.41   131.5 2457.94     136 2453.34   140.3 2452.03
   144.6 2451.81     150 2452.36   153.7 2453.34   156.2 2454.39   161.9 2457.25
   166.2 2458.56   168.4 2458.54   174.9 2457.78   187.8 2458.45   194.9 2457.76
   205.5 2457.64     216 2457.98   220.6 2458.38   226.6 2458.47   234.4 2459.11
#Mann= 5 ,-1,0
       0     .06       0      90     .07       0     136    .045       0
   153.7     .07       0     200     .06       0
#XS Ineff= 2 , 0
           133.5  2465.7     156          2466.4
Permanent Ineff=
       F       F
Bank Sta=136,153.7
XS Rating Curve= 0 ,0
Exp/Cntr(USF)=0,0
Exp/Cntr=0.5,0.3

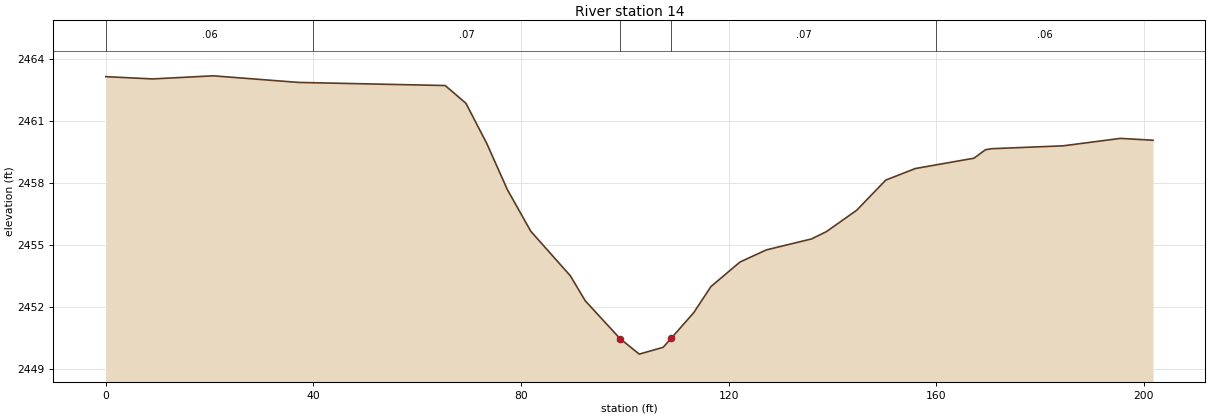
Type RM Length L Ch R = 1 ,14      ,,,
BEGIN DESCRIPTION:
structure xs 1
END DESCRIPTION:
XS GIS Cut Line= 5
2193293.07975139430279.1141882752193201.34311662430289.943334947
2193180.46875174430301.3905673042193153.36574572430328.156890021
2193115.15858767430356.350472378
#Sta/Elev= 30
       0 2463.14       9 2463.03    20.7 2463.18    37.2 2462.86    65.4 2462.71
    69.4 2461.85    73.4 2459.91    77.4 2457.66    81.9 2455.65    89.5  2453.5
    92.4 2452.28    99.1 2450.45   102.8  2449.7   107.4 2450.03  108.96 2450.47
   113.3 2451.71   116.6 2452.97   122.2 2454.16   127.3 2454.75     136 2455.28
   138.9 2455.64   144.7 2456.67   150.3 2458.13     156 2458.69   167.3 2459.19
   169.5  2459.6   170.7 2459.65   184.5 2459.79   195.5 2460.15   201.8 2460.06
#Mann= 5 ,-1,0
       0     .06       0      40     .07       0    99.1    .045       0
  108.96     .07       0     160     .06       0
Bank Sta=99.1,108.96
XS Rating Curve= 0 ,0
Exp/Cntr(USF)=0,0
Exp/Cntr=0.3,0.1
LCMann Table=0

Chan Stop Cuts=-1
Use User Specified Reach Order=0
Composite Channel Slope=5